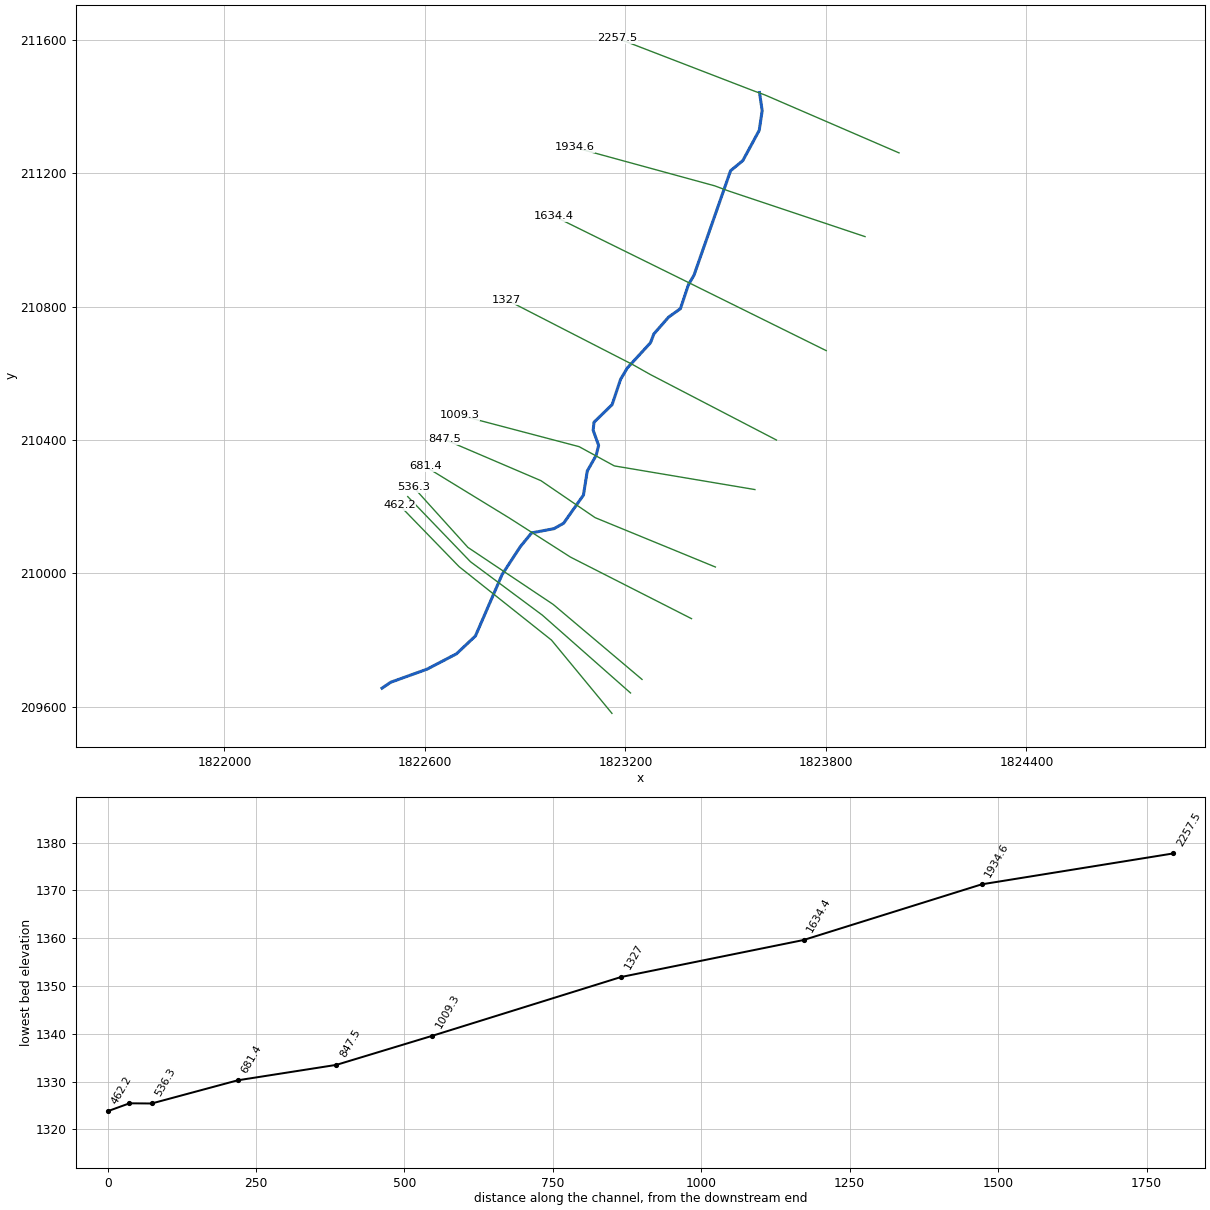
--- SugarRun.prj (project) ---

Proj Title=SugarRun
Current Plan=p01
Geom File=g01
Flow File=f01
Plan File=p01
DSS Export Rating Curves=0
DSS Export Rating Curve Sorted=0
DSS Export Volume Flow Curves=0
DXF OffsetX=0
DXF OffsetY=0
DXF ScaleX=0
DXF ScaleY=0

--- SugarRun.p01 (plan) ---

Plan Title=Floodplain
Program Version=4.00
Geom File=g01
Flow File=f01
K Sum by GR=0
Std Step Tol=0.01
Critical Tol=0.01
Num of Std Step Trials=20
Max Error Tol=0.3
Flow Tol Ratio=0.001
Split Flow NTrial=30
Split Flow Tol=0.02
Split Flow Ratio=0.02
Log Output Level=0
Friction Slope Method=1
Unsteady Friction Slope Method=2
Unsteady Bridges Friction Slope Method=1
Global Log Level=0
CheckData=False
Run HTab=0
Run UNet=0
Run PostProcess=0
UNET Theta=0
UNET Theta Warmup=0
UNET ZTol=0
UNET ZSATol=0
UNET MxIter=0
UNET MaxInSteps=0
UNET DtIC=0
UNET DtMin=0
UNET MaxCRTS=0
UNET WFStab=0
UNET SFStab=0
UNET WFX=0
UNET SFX=0
UNET DSS MLevel=0
UNET DZMax Abort=0
UNET Convert EG Bridges=0
UNET Use Existing IB Tables=0
UNET Froude Limit=0
UNET Froude Power=0
Write IC File=0
Echo Input=False
Echo Output=False
Write Detailed=0

--- SugarRun.f01 (steady flow) ---

Flow Title=NFF Regression Equation
Program Version=4.00
Number of Profiles=1
Profile Names=P100yr
River Rch & RM=SugarRun,Main      ,2257.5
565.6128
Boundary for River Rch & Prof#=SugarRun,Main      ,1
Up Type=0
Dn Type=3
Dn Slope=0.022925

--- SugarRun.g01 (geometry) ---

Geom Title=USGS 10m DEM
Program Version=4.00

River Reach=SugarRun     ,Main
Reach XY= 30
     1823601.226      211441.904     1823609.229      211387.710
     1823600.400      211328.426     1823551.207      211237.608
     1823514.628      211207.335     1823405.227      210894.128
     1823388.492      210865.508     1823364.526      210793.610
     1823329.208      210768.383     1823285.060      210717.928
     1823274.970      210691.440     1823205.595      210615.759
     1823185.413      210581.702     1823160.186      210506.020
     1823105.948      210453.043     1823103.425      210429.078
     1823119.822      210383.669     1823112.255      210353.396
     1823085.766      210306.726     1823074.414      210234.828
     1823015.130      210150.317     1822986.119      210133.920
     1822919.267      210121.306     1822885.210      210079.681
     1822830.972      209996.432     1822751.183      209812.159
     1822694.513      209758.713     1822606.402      209712.582
     1822497.533      209673.370     1822471.676      209655.628

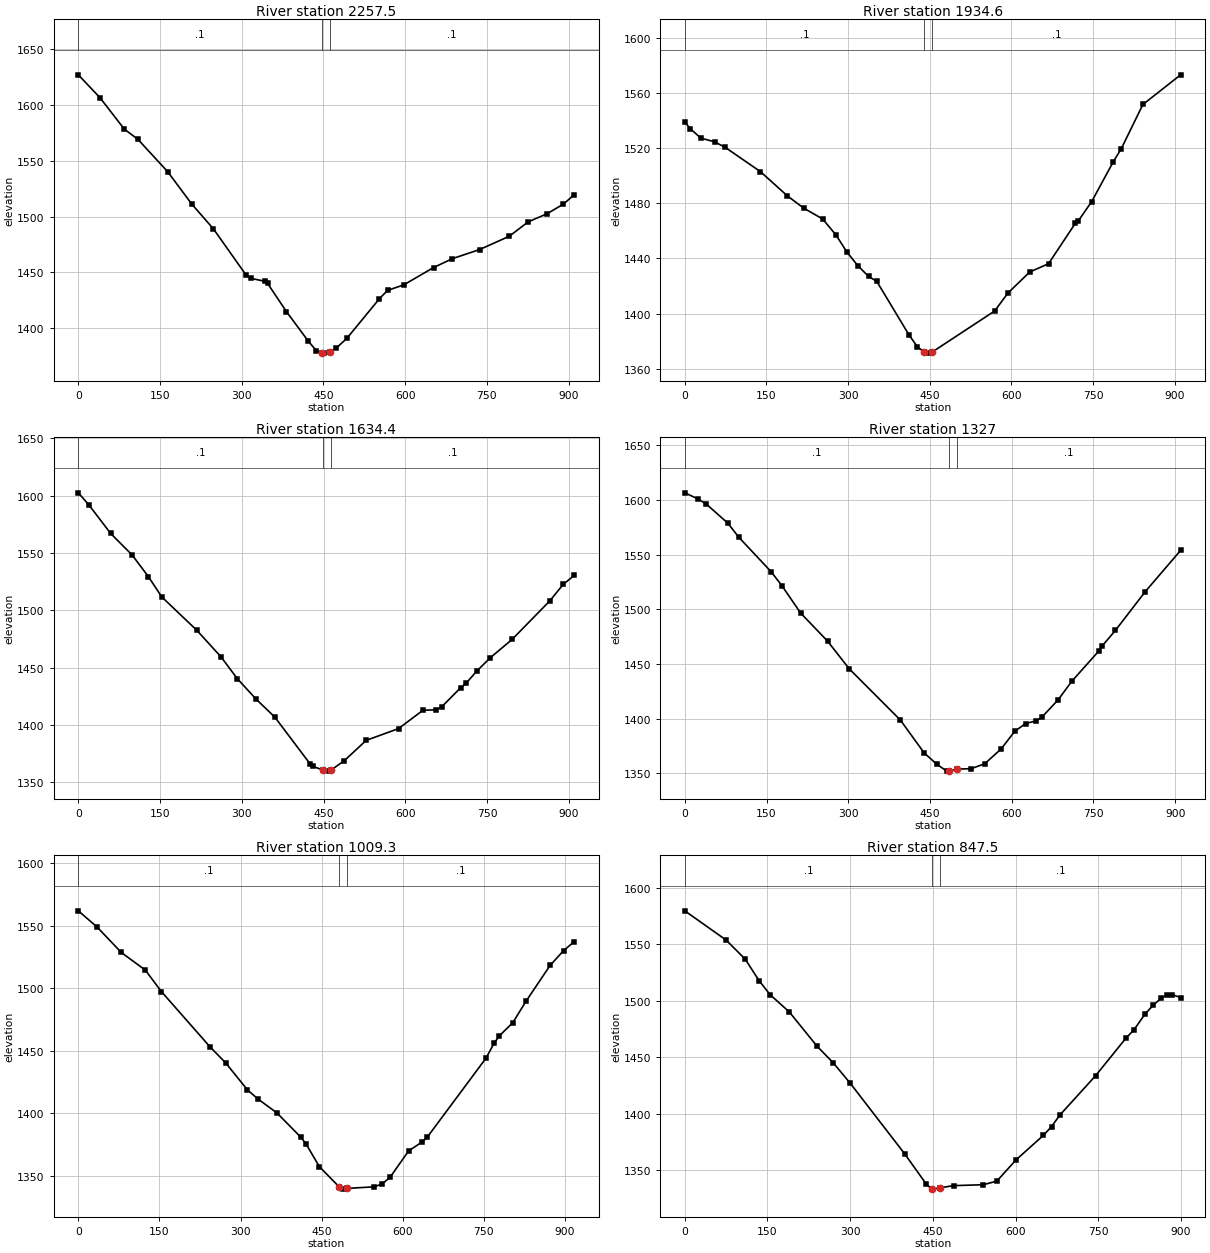
Type RM Length L Ch R = 1 ,2257.5,321.2,323,324
XS GIS Cut Line= 4
     1824018.775      211260.858     1823618.019      211434.379
     1823583.591      211446.992     1823176.126      211604.430
#Sta/Elev= 30
       0 1626.78    39.7 1606.34    84.4 1578.18   109.2 1569.11   163.8 1540.24
   208.4 1511.02   248.1 1488.86   307.7 1447.75   317.6 1444.56   342.4 1442.03
   347.4 1440.16   382.1 1414.83   421.8 1388.69   436.7 1380.03   446.9 1377.77
   450.5 1377.74   461.9 1378.90   473.4 1382.18   493.2 1391.11   552.8 1426.50
   567.7 1433.88   597.5 1438.84   652.1 1454.33   686.8 1462.29   736.5 1470.40
   791.1 1482.32   825.8 1495.20   860.6 1502.51   890.3 1511.05   910.2 1519.42
#Mann= 3 , 0 , 0
       0     0.1       0   446.9   0.045       0   461.9     0.1       0
Bank Sta=   446.9,   461.9
Exp/Cntr=0.3,0.1

Type RM Length L Ch R = 1 ,1934.6,302.8,300.1,297.8
XS GIS Cut Line= 4
     1823917.089      211009.815     1823507.597      211147.079
     1823467.156      211162.102     1823046.985      211277.297
#Sta/Elev= 30
       0 1539.17     9.9 1534.13    29.8 1527.27    54.6 1524.67    74.5 1520.54
   139.0 1502.99   188.6 1485.34   218.4 1476.52   253.2 1468.65   278.0 1456.85
   297.8 1444.60   317.7 1434.81   337.6 1426.90   352.5 1423.42   412.0 1384.36
   426.9 1376.02   439.2 1372.14   446.3 1371.27   454.2 1372.01   569.1 1401.84
   593.8 1415.00   633.4 1430.11   668.1 1436.18   717.6 1465.68   722.6 1467.17
   747.3 1481.23   786.9 1510.10   801.8 1519.72   841.4 1551.74   910.7 1573.27
#Mann= 3 , 0 , 0
       0     0.1       0   439.2   0.045       0   454.2     0.1       0
Bank Sta=   439.2,   454.2
Exp/Cntr=0.3,0.1

Type RM Length L Ch R = 1 ,1634.4,308.4,307.4,307.1
XS GIS Cut Line= 4
     1823800.888      210667.827     1823424.413      210854.367
     1823367.621      210882.587     1822985.294      211071.442
#Sta/Elev= 30
       0 1602.56    19.8 1591.76    59.3 1567.11    98.9 1548.22   128.5 1529.43
   153.2 1511.66   217.5 1482.54   262.0 1459.29   291.6 1440.42   326.2 1422.48
   360.8 1406.66   425.0 1366.14   429.9 1363.81   449.2 1360.61   459.2 1359.62
   464.2 1360.65   488.5 1368.86   528.2 1386.45   587.7 1396.76   632.3 1412.69
   657.1 1413.20   667.0 1415.77   701.8 1432.49   711.7 1436.33   731.5 1447.08
   756.3 1458.69   796.0 1474.55   865.4 1508.29   890.2 1522.79   910.0 1530.40
#Mann= 3 , 0 , 0
       0     0.1       0   449.2   0.045       0   464.2     0.1       0
Bank Sta=   449.2,   464.2
Exp/Cntr=0.3,0.1

Type RM Length L Ch R = 1 ,1327,317.4,317.7,317.4
XS GIS Cut Line= 4
     1823651.829      210399.852     1823274.466      210596.288
     1823222.182      210625.797     1822844.643      210820.031
#Sta/Elev= 30
       0 1606.65    24.7 1600.94    39.6 1596.30    79.2 1578.77    98.9 1566.10
   158.3 1534.49   178.1 1521.74   212.7 1496.52   262.2 1470.80   301.8 1445.53
   395.8 1398.55   439.3 1368.56   462.4 1358.24   480.8 1351.88   484.1 1351.93
   499.1 1353.74   525.4 1354.11   550.4 1358.60   580.4 1372.11   605.4 1388.22
   625.3 1395.45   645.3 1397.95   655.3 1401.23   685.3 1417.23   710.2 1434.10
   760.2 1462.03   765.2 1466.00   790.2 1480.64   845.1 1516.20   910.0 1553.96
#Mann= 3 , 0 , 0
       0     0.1       0   484.1   0.045       0   499.1     0.1       0
Bank Sta=   484.1,   499.1
Exp/Cntr=0.3,0.1

Type RM Length L Ch R = 1 ,1009.3,164,161.8,159.6
XS GIS Cut Line= 4
     1823587.494      210251.217     1823166.734      210322.193
     1823061.290      210379.914     1822703.213      210474.433
#Sta/Elev= 30
       0 1561.75    34.7 1548.80    79.4 1528.53   124.0 1514.40   153.8 1497.22
   243.1 1453.41   272.9 1440.19   312.6 1418.93   332.4 1411.48   367.2 1400.50
   411.8 1380.95   421.7 1375.36   445.9 1357.51     482 1341.62   489.2 1339.59
     497 1340.17   546.9 1341.42   561.7 1343.66   576.5 1348.92   611.1 1370.17
   635.8 1377.16   645.7 1381.21   754.3 1444.24   769.1 1456.06   779.0 1462.03
   803.7 1472.46   828.4 1489.73   872.8 1518.24   897.5 1529.90   917.2 1537.15
#Mann= 3 , 0 , 0
       0     0.1       0     482   0.045       0     497     0.1       0
Bank Sta=     482,     497
Exp/Cntr=0.3,0.1

Type RM Length L Ch R = 1 ,847.5,160.9,166.2,167.8
XS GIS Cut Line= 4
     1823469.273      210018.936     1823109.207      210167.048
     1822947.130      210277.923     1822658.677      210401.546
#Sta/Elev= 30
       0 1579.71    74.9 1553.86   109.8 1536.83   134.8 1517.89   154.7 1505.55
   189.7 1490.19   239.6 1460.12   269.5 1445.14   299.5 1427.56   399.2 1364.52
   438.4 1337.71   448.1 1333.55   448.2 1333.50   463.1 1334.68   487.5 1336.59
   541.5 1337.39   566.1 1340.58   600.7 1359.28   650.5 1381.06   665.4 1388.86
   680.4 1399.02   745.1 1433.76   799.9 1466.83   814.9 1474.50   834.8 1488.29
   849.7 1496.19   864.7 1502.58   874.6 1505.22   884.6 1505.50   899.5 1503.01
#Mann= 3 , 0 , 0
       0     0.1       0   448.1   0.045       0   463.1     0.1       0
Bank Sta=   448.1,   463.1
Exp/Cntr=0.3,0.1

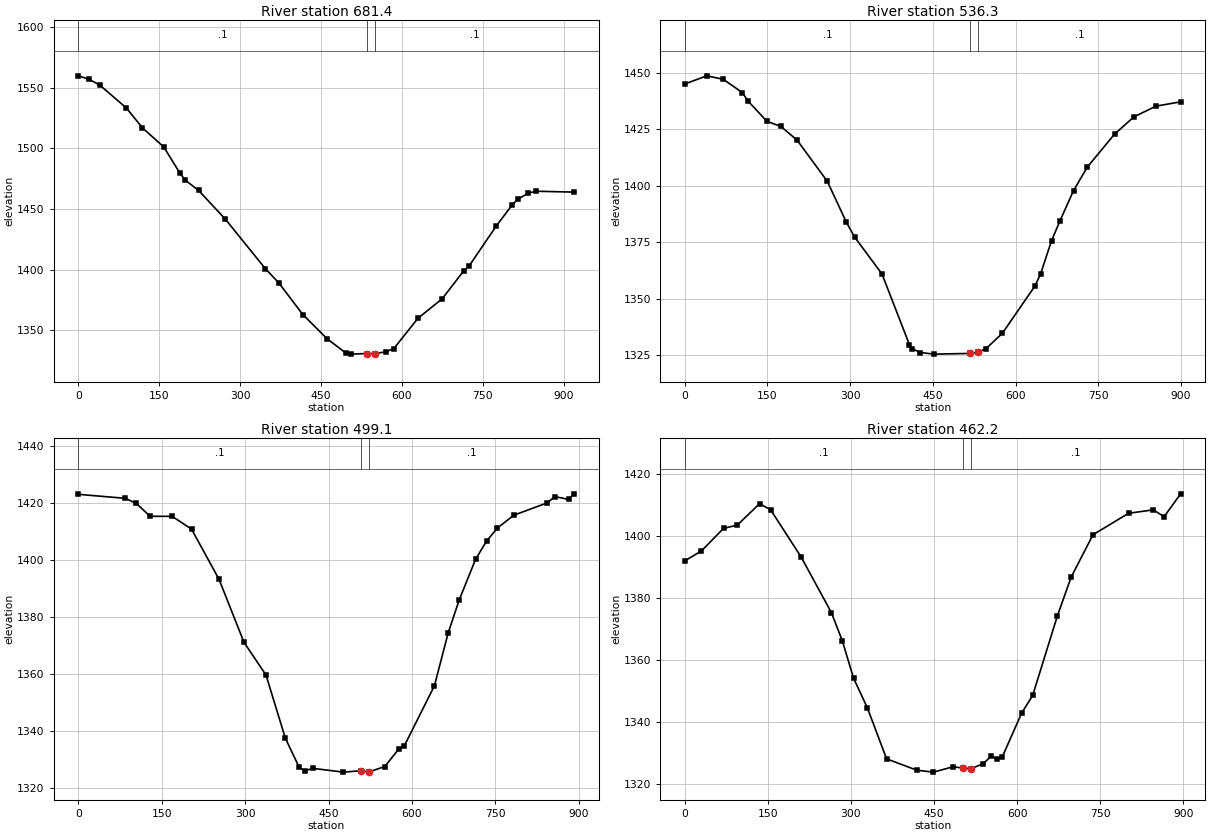
Type RM Length L Ch R = 1 ,681.4,149.7,145,143.9
XS GIS Cut Line= 4
     1823397.754      209864.090     1823035.547      210048.682
     1822851.683      210166.469     1822600.494      210320.542
#Sta/Elev= 30
       0 1559.67    19.8 1556.84    39.7 1552.08    89.2 1533.11   119.0 1516.74
   158.6 1500.96   188.4 1479.43   198.3 1473.64   223.1 1465.18   272.7 1441.50
   347.0 1400.64   371.8 1388.98   416.5 1362.85   461.1 1343.04   495.9 1331.25
   505.8 1330.27   534.5 1330.78   549.5 1330.70   570.3 1332.14   585.2 1334.88
   629.9 1359.82   674.8 1375.87   714.8 1398.91   724.8 1402.93   774.7 1435.63
   804.7 1453.30   814.7 1457.80   834.7 1463.02   849.6 1464.53   919.6 1463.82
#Mann= 3 , 0 , 0
       0     0.1       0   534.5   0.045       0   549.5     0.1       0
Bank Sta=   534.5,   549.5
Exp/Cntr=0.3,0.1

Type RM Length L Ch R = 1 ,536.3,38.5,37.3,36.1
XS GIS Cut Line= 4
     1823249.659      209681.853     1822984.078      209906.575
     1822728.713      210077.670     1822565.278      210258.980
#Sta/Elev= 30
       0 1445.03    39.8 1448.64    69.6 1447.12   104.4 1441.24   114.3 1437.58
   149.1 1428.46   174.0 1426.30   203.8 1420.13   258.4 1401.98   293.2 1383.76
   308.1 1377.24   357.8 1360.85   407.4 1329.65   412.4 1327.79   427.2 1326.14
   452.0 1325.42   516.8 1325.72   531.8 1326.29   546.2 1327.81   576.0 1334.63
   635.4 1355.66   645.4 1360.98   665.2 1375.58   680.2 1384.25   705.1 1397.80
   730.0 1408.20   779.8 1422.90   814.7 1430.46   854.6 1435.21   899.4 1437.12
#Mann= 3 , 0 , 0
       0     0.1       0   516.8   0.045       0   531.8     0.1       0
Bank Sta=   516.8,   531.8
Exp/Cntr=0.3,0.1

Type RM Length L Ch R = 1 ,499.1,37.5,36.8,36.2
XS GIS Cut Line= 4
     1823215.305      209641.173     1822951.346      209874.617
     1822736.211      210034.824     1822548.541      210230.123
#Sta/Elev= 30
       0 1423.12    84.4 1421.72   104.2 1419.94   129.0 1415.40   168.7 1415.38
   203.5 1410.90   253.1 1393.19   297.8 1371.12   337.5 1359.55   372.2 1337.39
   397.1 1327.16   407.0 1325.92   421.9 1326.78   476.6 1325.46   507.5 1325.93
   522.5 1325.53   551.1 1327.43   575.9 1333.54   585.8 1334.58   640.3 1355.83
   664.9 1374.36   684.6 1385.88   714.2 1400.27   733.9 1406.65   753.6 1411.30
   783.1 1415.79   842.2 1420.06   857.0 1422.31   881.6 1421.35   891.5 1423.30
#Mann= 3 , 0 , 0
       0     0.1       0   507.5   0.045       0   522.5     0.1       0
Bank Sta=   507.5,   522.5
Exp/Cntr=0.3,0.1

Type RM Length L Ch R = 1 ,462.2,469,462.2,455.4
XS GIS Cut Line= 4
     1823159.688      209580.020     1822978.698      209799.795
     1822702.295      210019.953     1822523.387      210204.590
#Sta/Elev= 30
       0 1391.92    30.0 1395.10    69.9 1402.37    94.9 1403.45   134.9 1410.33
   154.8 1408.40   209.8 1393.24   264.7 1375.22   284.7 1365.99   304.6 1354.11
   329.5 1344.58   364.3 1328.08   419.1 1324.41   449.0 1323.80   483.8 1325.50
   501.4 1325.16   516.4 1324.91   538.5 1326.48   553.5 1329.02   563.4 1327.90
   573.4 1328.78   608.2 1342.84   628.1 1348.53   672.7 1374.17   697.4 1386.61
   737.0 1400.33   801.2 1407.25   845.7 1408.35   865.5 1406.16   895.2 1413.52
#Mann= 3 , 0 , 0
       0     0.1       0   501.4   0.045       0   516.4     0.1       0
Bank Sta=   501.4,   516.4
Exp/Cntr=0.3,0.1